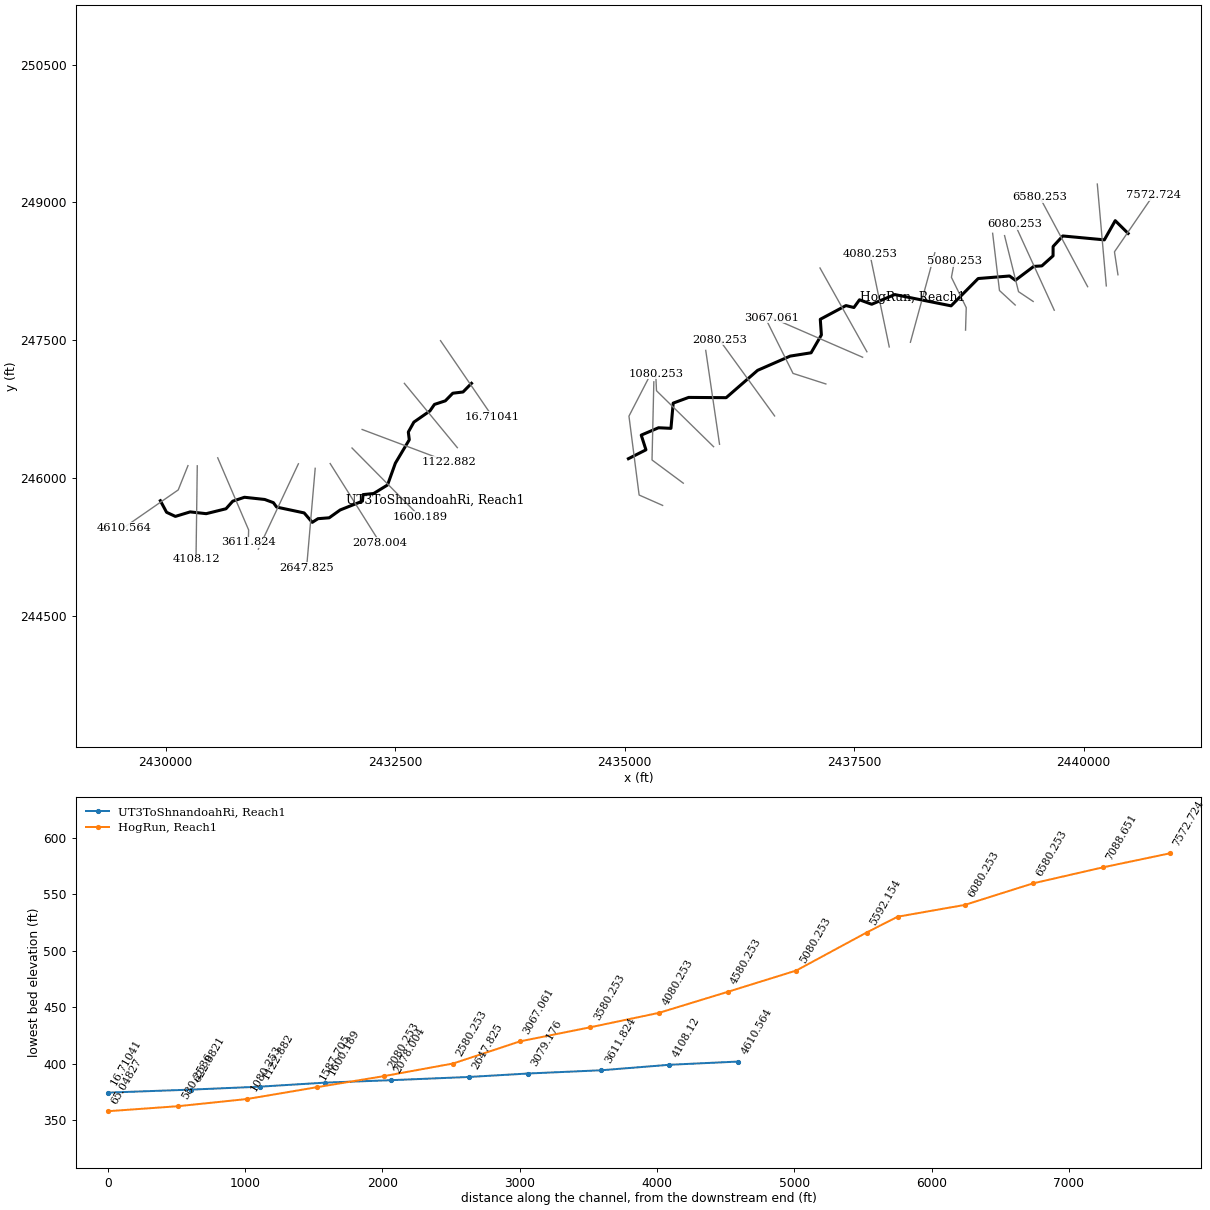
--- HogRun.prj (project) ---

Proj Title=HogRun
Current Plan=p01
Default Exp/Contr=0.3,0.1
English Units
Geom File=g01
Flow File=f01
Plan File=p01
Y Axis Title=Elevation
X Axis Title(PF)=Main Channel Distance
X Axis Title(XS)=Station
BEGIN DESCRIPTION:
END DESCRIPTION:
DSS Export Rating Curves= 0
DSS Export Rating Curve Sorted= 0
DSS Export Volume Flow Curves= 0
DXF OffsetX= 0
DXF OffsetY= 0
DXF ScaleX= 1
DXF ScaleY= 10

--- HogRun.p01 (plan) ---

Plan Title=Plan 01
Program Version=4.10
Short Identifier=Plan 01
Geom File=g01
Flow File=f01
Subcritical Flow
K Sum by GR= 0
Std Step Tol= 0.01
Critical Tol= 0.01
Num of Std Step Trials= 20
Max Error Tol= 0.3
Flow Tol Ratio= 0.001
Split Flow NTrial= 30
Split Flow Tol= 0.02
Split Flow Ratio= 0.02
Log Output Level= 0
Friction Slope Method= 1
Unsteady Friction Slope Method= 2
Unsteady Bridges Friction Slope Method= 1
Parabolic Critical Depth
Global Vel Dist= 0 , 0 , 0
Global Log Level= 0
CheckData=True
Encroach Param=-1 ,0,0, 0
Computation Interval=1HOUR
Output Interval=1HOUR
Run HTab= 0
Run UNet= 0
Run PostProcess= 0
Run WQNet= 0
UNET Theta= 1
UNET Theta Warmup= 1
UNET ZTol= 0.02
UNET ZSATol= 0.05
UNET MxIter= 20
UNET MaxInSteps= 0
UNET DtIC= 0
UNET DtMin= 0
UNET MaxCRTS= 20
UNET WFStab= 2
UNET SFStab= 1
UNET WFX= 1
UNET SFX= 1
UNET DSS MLevel= 4
UNET DZMax Abort= 100
UNET Convert EG Bridges= 0
UNET Use Existing IB Tables=-1
UNET Froude Reduction=False
UNET Froude Limit= 1
UNET Froude Power= 10
UNET Time Slicing=0,0, 5
UNET Junction Losses=0
Instantaneous Interval=1HOUR
Write IC File= 0
Write IC File at Sim End=0
Echo Input=False
Echo Parameters=False
Echo Output=False
Write Detailed= 0
WQ AD Non Conservative
WQ ULTIMATE=-1
WQ Max Comp Step=1HOUR
WQ Output Interval=15MIN
WQ Output Selected Increments= 0
WQ Output face flow=0
WQ Output face velocity=0
WQ Output face area=0
WQ Output face dispersion=0
WQ Output cell volume=0
WQ Output cell surface area=0
WQ Output cell continuity=0
WQ Output cumulative cell continuity=0
WQ Output face conc=0
WQ Output face dconc_dx=0
WQ Output face courant=0
WQ Output face peclet=0
WQ Output face adv mass=0
WQ Output face disp mass=0
WQ Output cell mass=0
WQ Output cell source sink temp=0
WQ Output cell source sink nsm=0
WQ Output MaxMinRange=-1
WQ Daily Max Min Mean=-1
WQ Daily Range=0
WQ Daily Time=0
WQ Create Restart=0
WQ Fixed Restart=0
WQ System Summary=0
WQ Use Fixed Temperature=0
Sorting and Armoring Iterations= 10
XS Update Threshold= 0.02
Hydraulics Update Threshold= 0.02
Energy Slope Method= 1
Volume Change Method= 0
XS Weighting Method= 0
Number of US Weighted Cross Sections= 1
Number of DS Weighted Cross Sections= 1
Upstream XS Weight=0.25
Main XS Weight=0.5
Downstream XS Weight=0.25
Number of DS XS's Weighted with US Boundary= 1
Upstream Boundary Weight= 1
Weight of XSs Associated with US Boundary= 0
Number of US XS's Weighted with DS Boundary= 1
Downstream Boundary Weight= 0.5
Weight of XSs Associated with DS Boundary= 0.5
Sediment Output Level= 4
Mass or Volume Output= 0
Output Increment Type= 1
Profile and TS Output Increment= 10
XS Output Flag= 0
XS Output Increment= 10
Disregard all LS=0
Disregard all Conn=0
Disregard all Breaches=0
Disregard all Pumps=0

--- HogRun.f01 (steady flow) ---

Flow Title=HogRun
Program Version=4.10
Number of Profiles= 1
Profile Names=PF 1
River Rch & RM=HogRun,Reach1          ,7572.724
     593
River Rch & RM=UT3ToShnandoahRi,Reach1          ,4610.564
    1571
Boundary for River Rch & Prof#=HogRun,Reach1          , 1
Up Type= 0
Dn Type= 3
Dn Slope=0.00886
Boundary for River Rch & Prof#=UT3ToShnandoahRi,Reach1          , 1
Up Type= 0
Dn Type= 3
Dn Slope=0.00439
DSS Import GetInterval= 0
DSS Import GetPeak= 0
DSS Import FillOption= 0

--- HogRun.g01 (geometry) ---

Geom Title=HogRun
Program Version=4.10

River Reach=UT3ToShnandoahRi,Reach1
Reach XY= 30
2429943.73123911245750.747267604 2430011.1799231245624.952899769
2430107.02946894245580.1107978522430268.12429111245629.206500188
2430442.72400753245609.8613945252430658.34890436 245663.24678643
2430732.17716877245745.7991147642430859.52074611245788.507362694
2431079.96354669245764.5490772722431174.88560094245729.653149679
2431209.78120044245681.606329769 2431509.7812566 245618.06446211
2431597.93232703245515.3300875132431660.17203194245555.304088935
 2431782.4660787245564.8536105162431901.83854336245650.226143181
2432144.75209953245746.4664362672432150.79703495245817.413472846
2432266.68230186245829.3927796042432417.80831194245922.367659271
2432503.01056936246159.6011086852432654.70317936246414.549089611
2432644.20812161246498.9308106012432704.70307936246606.996867433
2432879.44288737246728.6114536082432928.79154195 246799.83539252
2433047.15613461246838.6414172652433128.63267769246921.768219516
2433240.00417411 246935.165174352433332.46068211247029.253240764

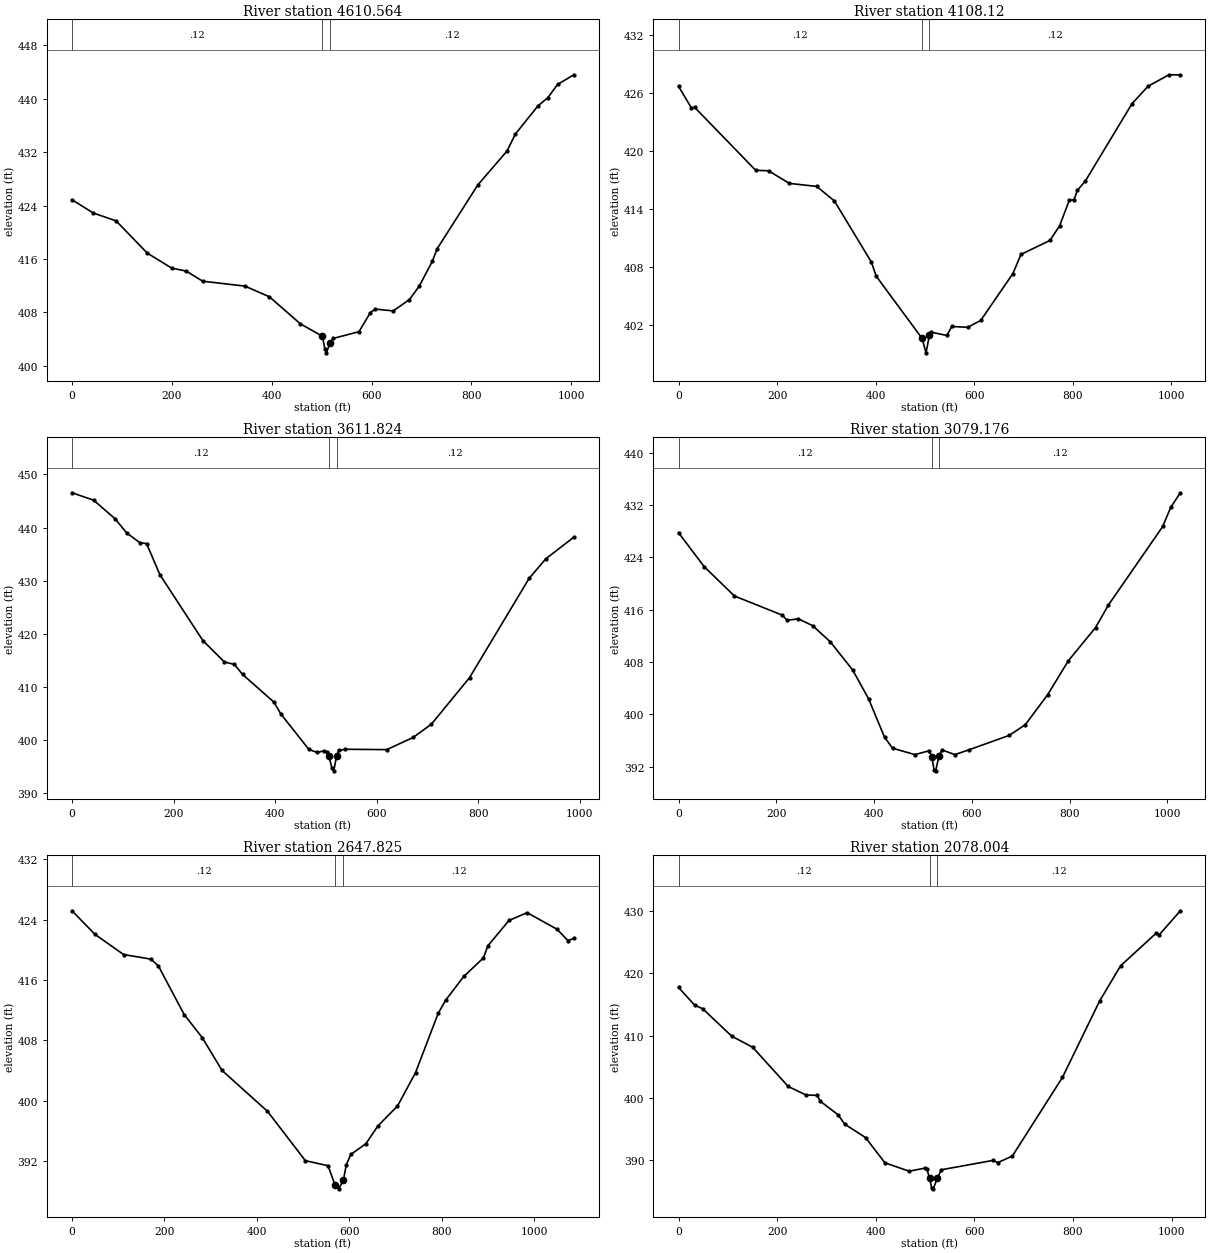
Type RM Length L Ch R = 1 ,4610.564,457.98,502.44,514.79
Node Name=980
XS GIS Cut Line= 4
2430244.13877478246132.6769499332430138.28268728245868.721113026
2429955.90805203245742.1767466812429546.07717878245457.806908607
#Sta/Elev= 30
       0  424.87    42.5  422.89   88.26  421.71  150.37   416.9   199.4  414.64
  228.82  414.19  261.51  412.68  346.41  411.94  395.38  410.34   457.4  406.29
  501.52  404.44  506.37  402.57  509.63  401.95  516.69  403.48  522.67   404.1
  574.84  405.12  597.66  407.99  607.44   408.5   643.3  408.23   675.9  409.93
  695.47  411.94  721.55  415.64  731.33  417.53  812.84   427.1  871.52  432.19
  887.82  434.69  933.47  438.95  953.03  440.15  972.59  442.14  1005.2  443.59
#Mann= 3 , 0 , 0
       0     .12       0  501.52    .045       0  516.69     .12       0
Bank Sta=501.52,516.69
XS Rating Curve= 0 ,0
Exp/Cntr=0.3,0.1

Type RM Length L Ch R = 1 ,4108.12 ,473.59,496.3,501.53
Node Name=981
XS GIS Cut Line= 3
2430345.66941161246131.1093677732430338.83970086245629.156959608
2430331.82035795245113.278070107
#Sta/Elev= 30
       0  426.71   26.08  424.46    32.6  424.53  156.47     418  182.55  417.95
  224.92  416.64  280.34  416.33  316.19  414.82  391.17  408.49  400.95  407.03
  494.14  400.57     502  399.08  508.96   400.9  511.79  401.23  544.45  400.88
  554.24  401.81   586.9  401.73  613.02  402.44  678.33   407.3  694.65  409.28
  753.43  410.73  773.02  412.24  792.62  414.89  802.41  414.96  808.94  415.91
  825.27  416.89  919.96  424.91  952.62  426.72  995.07   427.9 1017.92  427.89
#Mann= 3 , 0 , 0
       0     .12       0  494.14    .045       0  508.96     .12       0
Bank Sta=494.14,508.96
XS Rating Curve= 0 ,0
Exp/Cntr=0.3,0.1

Type RM Length L Ch R = 1 ,3611.824,532.65,532.65,485.44
Node Name=982
XS GIS Cut Line= 4
 2430568.3937037246218.2286161042430770.03995395245747.641630769
2430904.94716445245432.8053181922430901.48129211245299.177304611
#Sta/Elev= 30
       0  446.56   42.39  445.17   84.78  441.66  107.61  438.99   133.7  437.16
  146.74     437  172.83  431.17  257.62  418.75  300.01  414.72  319.57  414.27
  335.88  412.37  397.84  407.14  410.88  404.97  466.32  398.27  482.62   397.7
  495.67  397.99  502.19  397.71   505.7  396.96  511.97  394.71  515.23  394.24
  521.24  397.09  525.02  398.09  538.07   398.3  619.62  398.23  671.81  400.52
   707.7  403.03  782.73  411.77  900.14  430.46  932.74  434.12  988.17  438.21
#Mann= 3 , 0 , 0
       0     .12       0   505.7    .045       0  521.24     .12       0
Bank Sta=505.7,521.24
XS Rating Curve= 0 ,0
Exp/Cntr=0.3,0.1

Type RM Length L Ch R = 1 ,3079.176,408.6,431.35,431.29
Node Name=983
XS GIS Cut Line= 3
2431446.93000436246153.087014109 2431230.3408706245691.590233684
2431010.70417078245223.599371776
#Sta/Elev= 30
       0  427.77   52.29  422.59  114.38  418.09  212.41  415.16  222.22  414.37
  245.09   414.6   274.5  413.55  310.45  411.09   356.2  406.79  388.88  402.37
  421.56  396.49   437.9  394.82  483.65  393.84  513.07  394.44  518.15  393.52
  522.88  391.54  526.15  391.36  533.04  393.68  539.24  394.55  565.42  393.84
  594.86  394.59  676.66  396.78  709.38   398.4  755.19  402.98  797.73   408.2
  853.35  413.27  879.52   416.7  990.77  428.72 1007.13  431.64 1026.76  433.87
#Mann= 3 , 0 , 0
       0     .12       0  518.15    .045       0  533.04     .12       0
Bank Sta=518.15,533.04
XS Rating Curve= 0 ,0
Exp/Cntr=0.3,0.1

Type RM Length L Ch R = 1 ,2647.825,538.14,569.82,580.81
Node Name=984
XS GIS Cut Line= 3
2431629.94505827246103.7977426052431579.37330903 245519.23591961
2431536.35994361245022.045312941
#Sta/Elev= 30
       0  425.17   49.17  422.06  111.45  419.37  170.45  418.76  186.84  417.85
  242.57  411.41   281.9  408.33  324.51     404  422.85  398.58   504.8  392.04
  553.97  391.36  568.81  388.82  576.91   388.3  586.93  389.41  593.27  391.45
  603.05  392.86  635.67  394.27  661.76  396.64  704.17  399.28  743.31  403.72
  792.23  411.58  808.54  413.33  847.68  416.47  890.09  418.92  899.87  420.54
  945.54  423.89  984.68  424.92 1049.91   422.7 1072.74  421.22 1085.79   421.5
#Mann= 3 , 0 , 0
       0     .12       0  568.81    .045       0  586.93     .12       0
Bank Sta=568.81,586.93
XS Rating Curve= 0 ,0
Exp/Cntr=0.3,0.1

Type RM Length L Ch R = 1 ,2078.004,450.61,477.81,471.21
Node Name=985
XS GIS Cut Line= 3
2431793.13075553246155.5607624352432068.15710835245718.192870766
2432334.86195552245294.058220357
#Sta/Elev= 30
       0  417.75    32.7  414.91   49.05  414.33  107.91  409.93  150.42  408.15
  222.36  401.87  258.33   400.5  281.22  400.43  287.76  399.48  323.73  397.31
  336.81  395.83  379.31  393.66  418.55  389.62   467.6  388.27   500.3  388.77
  503.57  388.61  509.07  387.18  513.38  385.59  516.65  385.44   524.7  387.13
  533.03   388.5  637.81     390  647.64  389.65  677.11  390.71  778.62  403.32
  853.94  415.57  896.51  421.22  968.55  426.45   975.1  426.21 1017.67  430.05
#Mann= 3 , 0 , 0
       0     .12       0  509.07    .045       0   524.7     .12       0
Bank Sta=509.07,524.7
XS Rating Curve= 0 ,0
Exp/Cntr=0.3,0.1

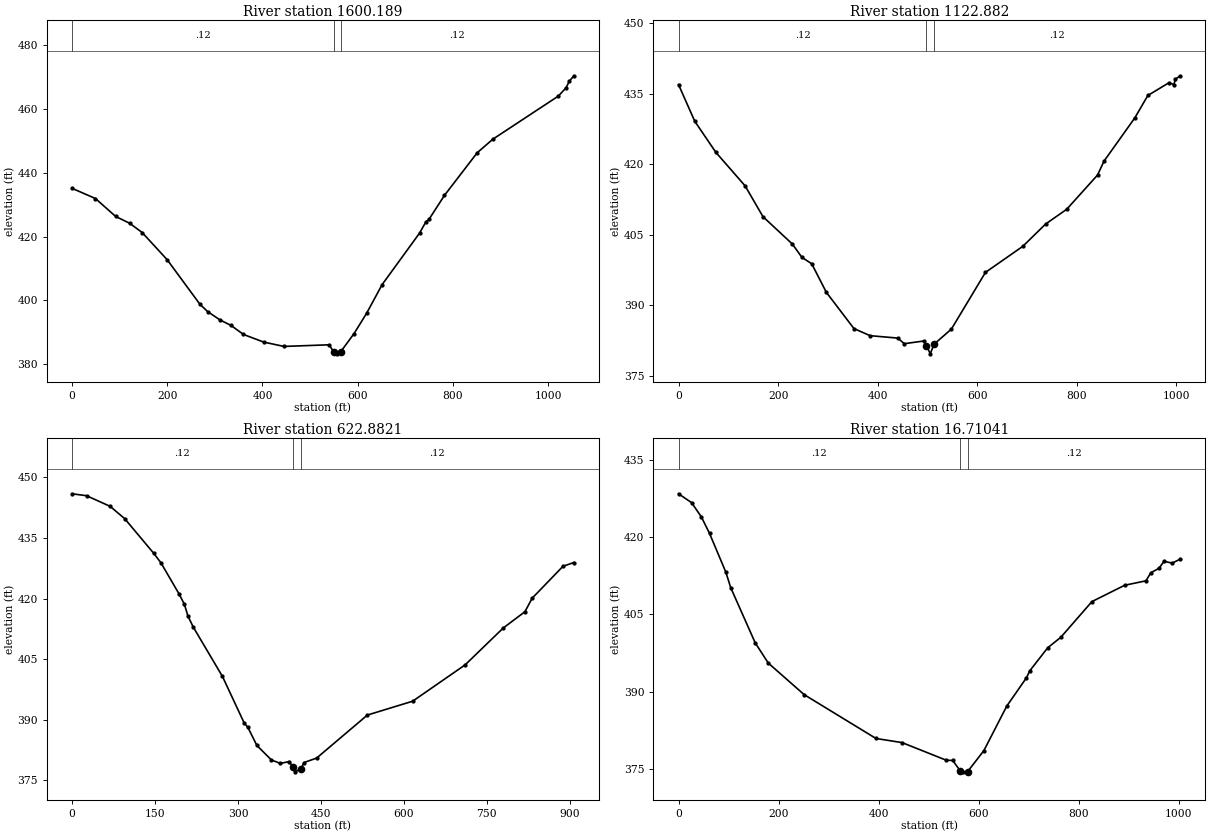
Type RM Length L Ch R = 1 ,1600.189,460.08,477.31,487.93
Node Name=986
XS GIS Cut Line= 3
2432030.97640844246325.0922475162432419.93265152245931.719346598
2432772.17046411245575.481542021
#Sta/Elev= 30
       0   435.1    49.1  431.91   91.65  426.29  121.11  424.15   147.3  421.26
  199.68  412.77  268.42  398.84  284.78  396.51  310.97  393.88  333.88  392.18
  360.07  389.35  402.62  386.96  445.18   385.6  540.11  386.11  549.71  383.87
  556.47  383.28  564.75  384.01  592.49  389.64  618.69  395.96  651.43  404.97
  730.01  421.08  743.11  424.54  749.66  425.35   782.4  432.91  851.17  446.25
  883.91  450.48 1021.43  463.97  1037.8  466.58 1044.35  468.59 1054.17  470.34
#Mann= 3 , 0 , 0
       0     .12       0  549.71    .045       0  564.75     .12       0
Bank Sta=549.71,564.75
XS Rating Curve= 0 ,0
Exp/Cntr=0.3,0.1

Type RM Length L Ch R = 1 ,1122.882,505.11,500,472.76
Node Name=987
XS GIS Cut Line= 3
2432141.09265803246526.7673691062432614.49558261246348.847449347
2433084.70756869 246172.12667419
#Sta/Elev= 30
       0  436.96   32.63  429.16   75.04  422.55  133.77  415.42  169.67  408.87
   228.4  403.08  247.97  400.21  267.55  398.86  296.91  392.79  352.38  385.07
  385.01  383.56  440.48  383.05  453.53  381.86  492.68  382.43  498.13  381.45
  505.73   379.7  513.23  381.74  548.14  384.96  616.64  397.03  691.66  402.57
  737.32   407.3  779.73  410.44   841.7  417.72  854.75  420.68  916.73   429.9
  942.82  434.65  985.23  437.36  995.01  436.97  998.27  438.13 1008.06  438.84
#Mann= 3 , 0 , 0
       0     .12       0  498.13    .045       0  513.23     .12       0
Bank Sta=498.13,513.23
XS Rating Curve= 0 ,0
Exp/Cntr=0.3,0.1

Type RM Length L Ch R = 1 ,622.8821,591.2,606.17,593.06
Node Name=988
XS GIS Cut Line= 3
2432601.26430985247029.0285036862432859.49213986246715.530114934
2433178.05219828246328.786465853
#Sta/Elev= 30
       0  445.96    26.2  445.48   68.78  442.85   94.99  439.82   147.4  431.26
   160.5   428.9  193.25   421.2  203.08  418.59  209.63  415.62  219.46  412.86
  271.86  400.73  311.17   389.2  317.72  388.14   334.1  383.64   360.3  380.05
  376.68  379.18  393.05  379.66  398.83  378.24  402.88   377.1   413.9  377.87
  419.26   379.4  442.18  380.51  533.88  391.16  615.75  394.59  710.72   403.6
  779.49  412.71  818.79  416.76  831.88  420.11  887.56     428  907.21  428.94
#Mann= 3 , 0 , 0
       0     .12       0  398.83    .045       0   413.9     .12       0
Bank Sta=398.83,413.9
XS Rating Curve= 0 ,0
Exp/Cntr=0.3,0.1

Type RM Length L Ch R = 1 ,16.71041,26.91,16.71,14.22
Node Name=989
XS GIS Cut Line= 3
2432994.96496603247494.2250798492433278.49031761 247079.58942619
2433561.13214077246666.245436609
#Sta/Elev= 30
       0  428.36   26.09  426.64   45.66  423.87   61.97  420.67   94.59  413.15
  104.37  410.14   153.3  399.45  179.39  395.53  251.15  389.41  394.67  380.91
  446.85  380.11  535.03   376.7  548.12  376.64  562.75  374.68  567.76  374.44
  577.71  374.47  610.31  378.55  656.12  387.19   695.4  392.67  701.94  394.01
  737.94   398.5  764.13  400.53  826.31  407.45  891.77  410.62  934.31  411.48
  944.13  413.05  960.49  413.91  970.31  415.26  986.68  414.92 1003.04  415.69
#Mann= 3 , 0 , 0
       0     .12       0  562.75    .045       0  577.71     .12       0
Bank Sta=562.75,577.71
XS Rating Curve= 0 ,0
Exp/Cntr=0.3,0.1

River Reach=HogRun          ,Reach1
Reach XY= 30
2440483.92735028248662.1633607752440343.43156828248801.084998935
2440224.94197586248592.1008368582439772.03376094248634.418337524
2439666.73869595248519.661349192 2439666.2180277248418.098888263
2439544.00436136248308.3333597632439455.72304186248302.734289601
2439256.20047502 248152.47409144 2439192.1815742248198.480889186
2438850.49295311248170.8116531822438555.76453994247873.368678525
2437942.01872019247996.1968449352437691.08549502247890.662935272
2437558.14284752247939.2307515142437497.37886144247855.203032434
2437410.27503303247876.1718225182437131.06496152247726.801058263
2437143.06592177 247556.27613686 2437030.9673927247362.070160434
2436803.14829452247326.0538282692436448.42590685247170.906500772
 2436106.0105812246873.1849833582435697.33456127246876.049478933
2435528.98548852246813.9259155242435504.66959228246539.131189525
2435369.25286835246545.6416751892435180.97174886246465.433174193
2435232.27381161 246305.276998432435041.38836661246208.662362263

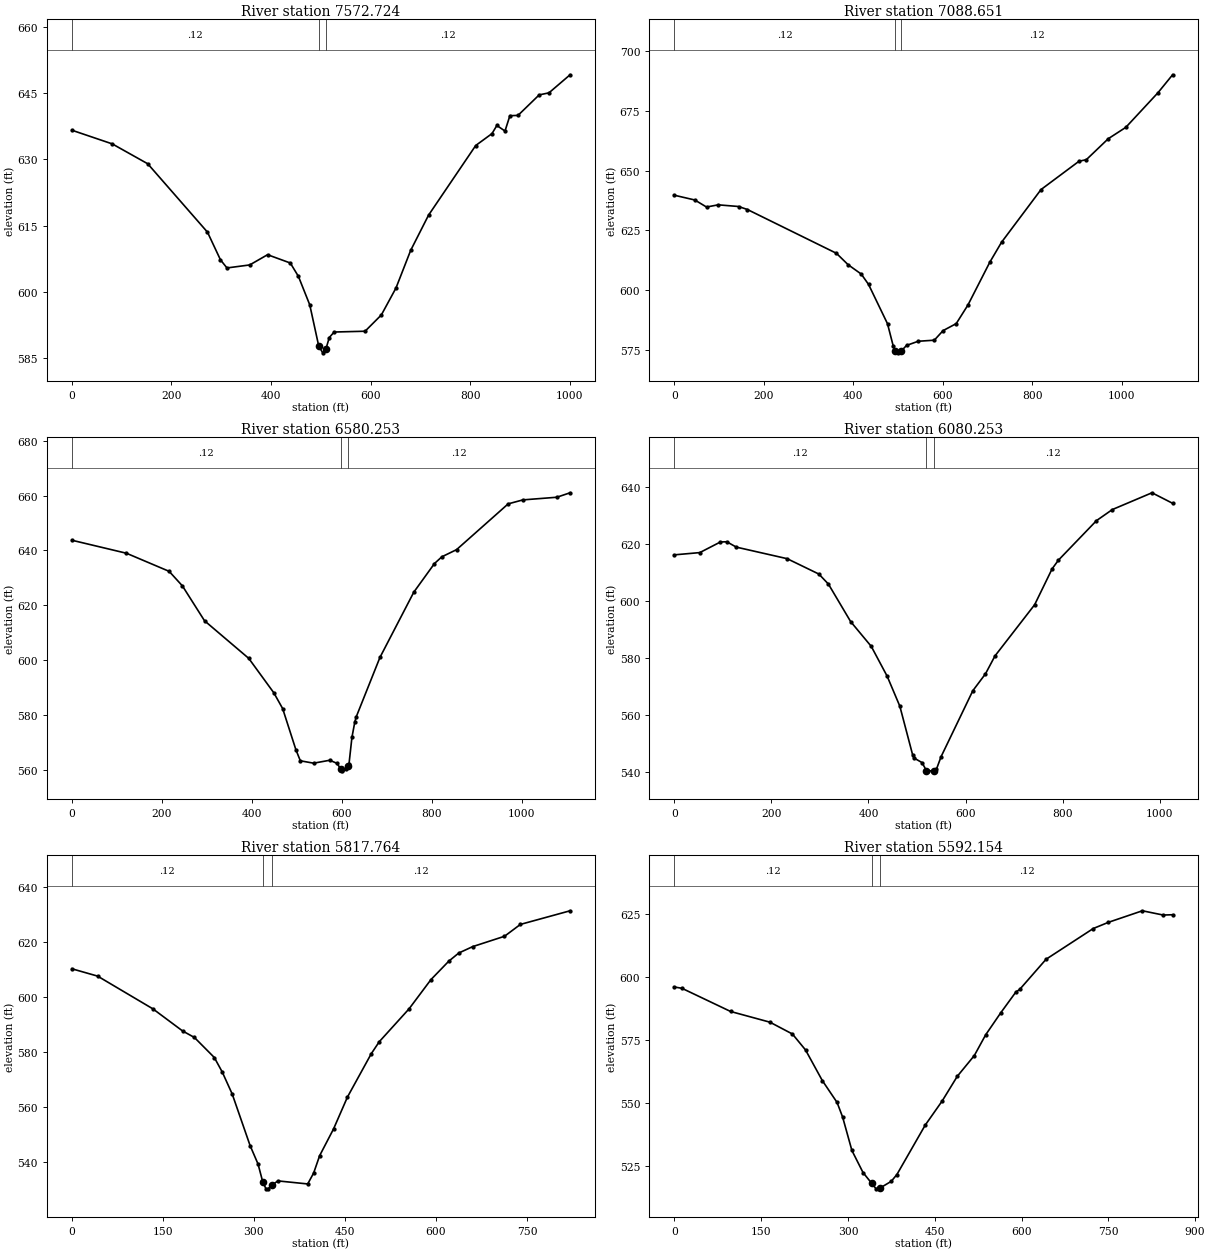
Type RM Length L Ch R = 1 ,7572.724,460.3,484.07,495.97
Node Name=964
XS GIS Cut Line= 4
2440373.05880561248211.7669518592440334.97587653248461.746110693
2440475.18360136248666.1728671942440758.06558153249078.622829691
#Sta/Elev= 30
       0  636.64   81.05  633.54  152.37  629.03  272.43  613.52  298.53  607.24
  311.57  605.41  357.24  606.09  393.12  608.41  438.78  606.53  455.09   603.5
  477.92  597.03  496.05  587.63  504.02  586.16  510.42  587.05   517.1  589.63
   526.9  590.88  589.01  591.06   621.7  594.75  651.12  600.86  680.54  609.37
   716.5  617.37  811.29  633.17  843.98  635.87  853.79  637.71  870.13  636.45
  879.94  639.93  896.28     640  938.78  644.65  958.39  645.11 1000.89  649.21
#Mann= 3 , 0 , 0
       0     .12       0  496.05    .045       0  510.42     .12       0
Bank Sta=496.05,510.42
XS Rating Curve= 0 ,0
Exp/Cntr=0.3,0.1

Type RM Length L Ch R = 1 ,7088.651,486.56,508.4,511.17
Node Name=965
XS GIS Cut Line= 3
2440246.10728785248090.5126011822440202.15921302248587.714034602
2440148.07172278249199.628165096
#Sta/Elev= 30
       0   639.7   45.67  637.71   71.77  634.77   97.87  635.69  143.54  634.99
  163.12  633.74  362.12  615.44  388.22  610.67  417.58  606.76  433.89  602.44
   476.3  585.99  489.35  576.49   493.2  574.52  499.14  573.84  507.07  574.61
  518.75  576.93  544.89  578.68  580.83  579.12  600.43  583.12  629.84  586.05
  655.98   593.8  704.99  611.73  731.14  620.05  819.36  642.07  904.31  653.91
  920.65  654.56  969.66  663.32 1008.88  668.07 1080.76  682.54 1113.44  690.04
#Mann= 3 , 0 , 0
       0     .12       0   493.2    .045       0  507.07     .12       0
Bank Sta=493.2,507.07
XS Rating Curve= 0 ,0
Exp/Cntr=0.3,0.1

Type RM Length L Ch R = 1 ,6580.253,494.95,500,487.24
Node Name=966
XS GIS Cut Line= 3
2440042.94988577248081.6668183512439756.84579919248616.259581193
2439520.20060319249058.437174514
#Sta/Elev= 30
       0  643.72  121.27  638.98  216.31  632.38  245.81  627.07  294.97  614.37
   393.3  600.67  449.02  588.13  468.68  582.38  498.18  567.36  508.01  563.35
  537.51  562.48  573.56  563.55  589.95  562.39  598.24   560.2  599.78  559.69
  609.61  560.35  613.92  561.58  616.17   562.1  622.73  571.86  629.28  577.61
  632.56  579.47  685.01  601.01   760.4  624.81  806.29  635.23  822.68  637.68
  855.46  640.29  970.18  656.97 1002.96  658.42 1078.35  659.38 1107.86  661.01
#Mann= 3 , 0 , 0
       0     .12       0  598.24    .045       0  613.92     .12       0
Bank Sta=598.24,613.92
XS Rating Curve= 0 ,0
Exp/Cntr=0.3,0.1

Type RM Length L Ch R = 1 ,6080.253,486.92,488.1,473.12
Node Name=967
XS GIS Cut Line= 3
2439679.25146618247825.9238915152439460.08720636248304.960335016
2439252.08106069248759.608047768
#Sta/Elev= 30
       0  616.32   52.35  617.11   94.89  620.84  107.98  620.91  127.61  619.03
  232.31  614.98  297.75  609.58  317.38  606.07  363.19  592.91  405.73   584.2
  438.45  573.75  464.62  563.21   490.8  546.26  494.07  545.01  510.43  543.41
  519.28  540.64  523.52  540.53  534.17  540.55  539.86  541.01  549.66  545.51
  615.02  568.64  641.16  574.58  660.77  580.87  742.46  598.82  778.41   611.4
  791.48  614.46  869.91  628.33  902.58  632.21  984.28   638.1 1026.76  634.41
#Mann= 3 , 0 , 0
       0     .12       0  519.28    .045       0  534.17     .12       0
Bank Sta=519.28,534.17
XS Rating Curve= 0 ,0
Exp/Cntr=0.3,0.1

Type RM Length L Ch R = 1 ,5817.764,222.04,225.61,218.89
XS GIS Cut Line= 3
2439449.72863127247921.1297378542439290.00650978248027.900521681
2439138.09670861248638.143723771
#Sta/Elev= 30
       0  610.19   42.33  607.53  133.51  595.61  182.35  587.58  201.95  585.19
   234.7  577.91   247.8  572.62  264.18  564.63  293.66  545.87  306.76  539.15
  314.65  532.54  319.86  530.15  323.14  530.12   330.1  531.53  339.51  533.01
  388.64   531.9  398.47  535.91   408.3   542.2  431.22  551.93  454.15  563.54
  493.46  579.33  506.56  583.66  555.69  595.63  591.72  606.26  621.19  612.98
  637.57  615.93   660.5  618.26   712.9  622.02  739.11  626.34  820.99   631.3
#Mann= 3 , 0 , 0
       0     .12       0  314.65    .045       0   330.1     .12       0
Bank Sta=314.65,330.1
XS Rating Curve= 0 ,0
Exp/Cntr=0.3,0.1

Type RM Length L Ch R = 1 ,5592.154,497.56,511.9,516.46
Node Name=968
XS GIS Cut Line= 4
 2439253.9038917247882.1734509322439082.53973311248040.296166182
2439070.41475736248142.0151228612439008.21606286248663.810667187
#Sta/Elev= 30
       0  596.16   12.95  595.66   97.15  586.46  165.16  582.21  204.02  577.52
  226.69  571.19  255.58  559.09  281.19  550.38  290.79  544.57   306.8  531.34
  326.01   522.6  341.13  518.28  348.67  516.13  356.06  516.54  374.78   519.1
  384.57   521.8  433.53   541.4   462.9  550.99  489.01  560.77  518.39  568.98
  537.97  577.19  564.08  585.94  590.19  594.17  596.72  595.18  642.42  607.17
  724.02  619.36  750.13  621.81  808.88  626.39  844.78   624.7   861.1  624.82
#Mann= 3 , 0 , 0
       0     .12       0  341.13    .045       0  356.06     .12       0
Bank Sta=341.13,356.06
XS Rating Curve= 0 ,0
Exp/Cntr=0.3,0.1

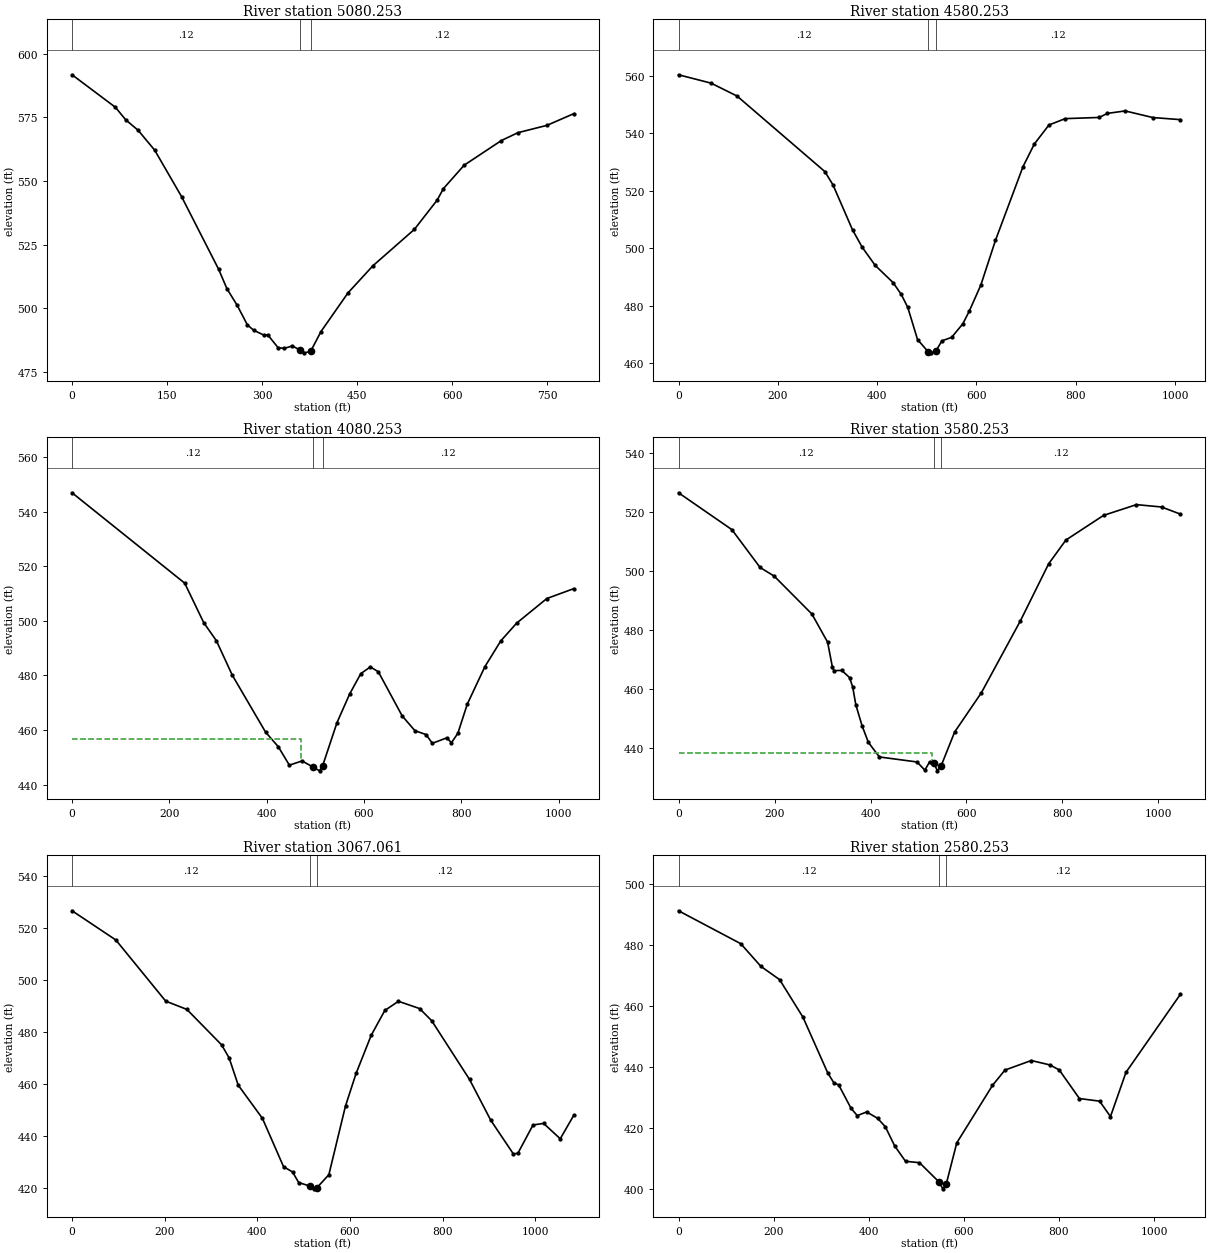
Type RM Length L Ch R = 1 ,5080.253,519.23,500,476.91
Node Name=969
XS GIS Cut Line= 5
2438713.19204661247609.2307553592438720.71663786247853.603626192
2438664.17114727247969.2887622712438559.22745952248183.990104526
2438592.35862686248360.619672522
#Sta/Elev= 30
       0   591.7   68.46  578.92   84.76  573.99  104.32  569.89  130.39  562.09
  172.77  543.87  231.45  515.25  244.49  507.65  260.58  501.16  276.68  493.48
  286.34  491.42  302.43  489.48  308.87  489.56  324.97  484.58  334.62  484.23
   347.5  485.21  360.38  483.54  366.82   482.5  376.53  483.09   392.9  490.88
  435.45  506.04  474.74  516.68  540.21  530.98  576.22  542.48  586.04  546.99
  618.76  556.18  677.58  565.88  703.72  568.96  749.46  571.84  791.94  576.44
#Mann= 3 , 0 , 0
       0     .12       0  360.38    .045       0  376.53     .12       0
Bank Sta=360.38,376.53
XS Rating Curve= 0 ,0
Exp/Cntr=0.3,0.1

Type RM Length L Ch R = 1 ,4580.253,485.04,500,513.23
Node Name=970
XS GIS Cut Line= 3
 2438112.6361611247476.8602851932438247.05190277247969.620126441
2438378.55984186248451.719884023
#Sta/Elev= 30
       0  560.44   65.48  557.53  117.87  553.03  294.67  526.73  311.04  522.09
  350.33  506.45  369.98  500.35  396.17  494.03  432.18  488.05  448.56  483.94
  461.65  479.42   481.3  468.23  503.25  463.87  507.49  463.61  518.23  464.22
  530.36  467.79  549.96     469  572.82   473.8  585.88   478.3  608.75   487.2
  638.14  502.75  693.67  528.44  716.53  536.35  745.92  542.95  778.58  545.17
  847.17  545.58   863.5  546.99  899.43  547.85  954.95  545.55 1010.48  544.82
#Mann= 3 , 0 , 0
       0     .12       0  503.25    .045       0  518.23     .12       0
Bank Sta=503.25,518.23
XS Rating Curve= 0 ,0
Exp/Cntr=0.3,0.1

Type RM Length L Ch R = 1 ,4080.253,477.57,500,500.13
Node Name=971
XS GIS Cut Line= 3
2437882.13826253247425.8479200152437778.32416569 247923.79672727
2437671.60554712248435.678905606
#Sta/Elev= 30
       0  546.91   231.5  513.81  270.63  499.34  296.72   492.7  329.32   480.1
  397.79  459.22  423.88   453.9   446.7  447.11  472.79  448.67  495.61  446.39
  508.66  445.04  515.19  446.94   544.6   462.7  570.75  473.23  593.62  480.67
  613.23  483.11  629.57  481.34  678.59  465.17  704.74  459.76  727.62  458.33
  740.69  455.13   770.1  457.11   779.9  455.36  792.98  458.75  812.58  469.53
  848.53  483.17  881.21  492.62  913.89  499.15  975.99  508.17 1031.54   511.8
#Mann= 3 , 0 , 0
       0     .12       0  495.61    .045       0  515.19     .12       0
#XS Ineff= 2 , 0
          471.21  456.83
Permanent Ineff=
       F       F
Bank Sta=495.61,515.19
XS Rating Curve= 0 ,0
Exp/Cntr=0.3,0.1

Type RM Length L Ch R = 1 ,3580.253,485.33,513.19,524.89
Node Name=972
XS GIS Cut Line= 3
 2437638.6866497247373.4789302652437375.15764919247844.133172691
2437127.86778945248285.784848437
#Sta/Elev= 30
       0  526.59  111.15  514.09     170  501.25  199.42  498.31  277.88  485.47
  310.57  475.94  320.38  467.66  323.65  466.25  339.99  466.35  356.34  463.92
  362.88  460.73  369.41  454.69  382.49  447.54  395.57  441.94  418.45  436.99
  496.91  435.29  513.26  432.51  523.06   435.3  532.22  434.85  539.41  432.28
  547.09  433.94  575.33  445.45  630.85  458.72  712.49   483.2  771.27  502.52
  807.19  510.56  885.57  518.92  954.14  522.57 1006.39  521.77 1045.58  519.36
#Mann= 3 , 0 , 0
       0     .12       0  532.22    .045       0  547.09     .12       0
#XS Ineff= 2 , 0
             528  438.39
Permanent Ineff=
       F       F
Bank Sta=532.22,547.09
XS Rating Curve= 0 ,0
Exp/Cntr=0.3,0.1

Type RM Length L Ch R = 1 ,3067.061,502.52,486.81,457.22
Node Name=973
XS GIS Cut Line= 3
2437592.01023386247313.5866616072437116.39274678247520.307048693
2436598.26681453247745.502792522
#Sta/Elev= 30
       0  526.61   94.59  515.38  202.22  491.89  247.88  488.72   322.9   475.1
  339.21  470.06  358.78  459.61  410.97  446.88  456.63   428.3   476.2  426.24
  489.25  422.21  513.96  420.81  521.87  419.78  528.86  420.23  554.52  425.22
  590.44  451.63   613.3  464.12  645.96  478.78  675.35  488.31  704.74  491.84
  750.46  489.04  776.58  484.37  858.22  461.82  903.94  446.18  952.92  433.19
  962.72  433.46  995.37  444.31 1018.23  444.92 1054.16  439.01 1083.55  448.09
#Mann= 3 , 0 , 0
       0     .12       0  513.96    .045       0  528.86     .12       0
Bank Sta=513.96,528.86
XS Rating Curve= 0 ,0
Exp/Cntr=0.3,0.1

Type RM Length L Ch R = 1 ,2580.253,490.79,500,500.3
Node Name=974
XS GIS Cut Line= 4
2437191.83780585247022.482913107 2436834.0639151247137.647052854
 2436753.8321202247298.494828269 2436530.9467392247745.332189187
#Sta/Elev= 30
       0  491.34  130.73  480.56  173.22  473.11  212.44  468.78  261.46   456.5
  313.75  438.17  326.83  434.88  336.63  434.29  362.78  426.56  375.85   424.2
  395.46   425.4  418.34  423.34  434.68  420.58  454.29   414.3  477.16  409.23
  506.58  408.77   547.7  402.44   555.6   400.2  562.66  401.67  584.97  415.27
  660.04   434.1  686.15  439.12  741.63  442.26  780.79  440.81  800.38  439.17
   842.8   429.8  885.23  428.94  908.08  423.88  940.71  438.39 1054.94  463.93
#Mann= 3 , 0 , 0
       0     .12       0   547.7    .045       0  562.66     .12       0
Bank Sta=547.7,562.66
XS Rating Curve= 0 ,0
Exp/Cntr=0.3,0.1

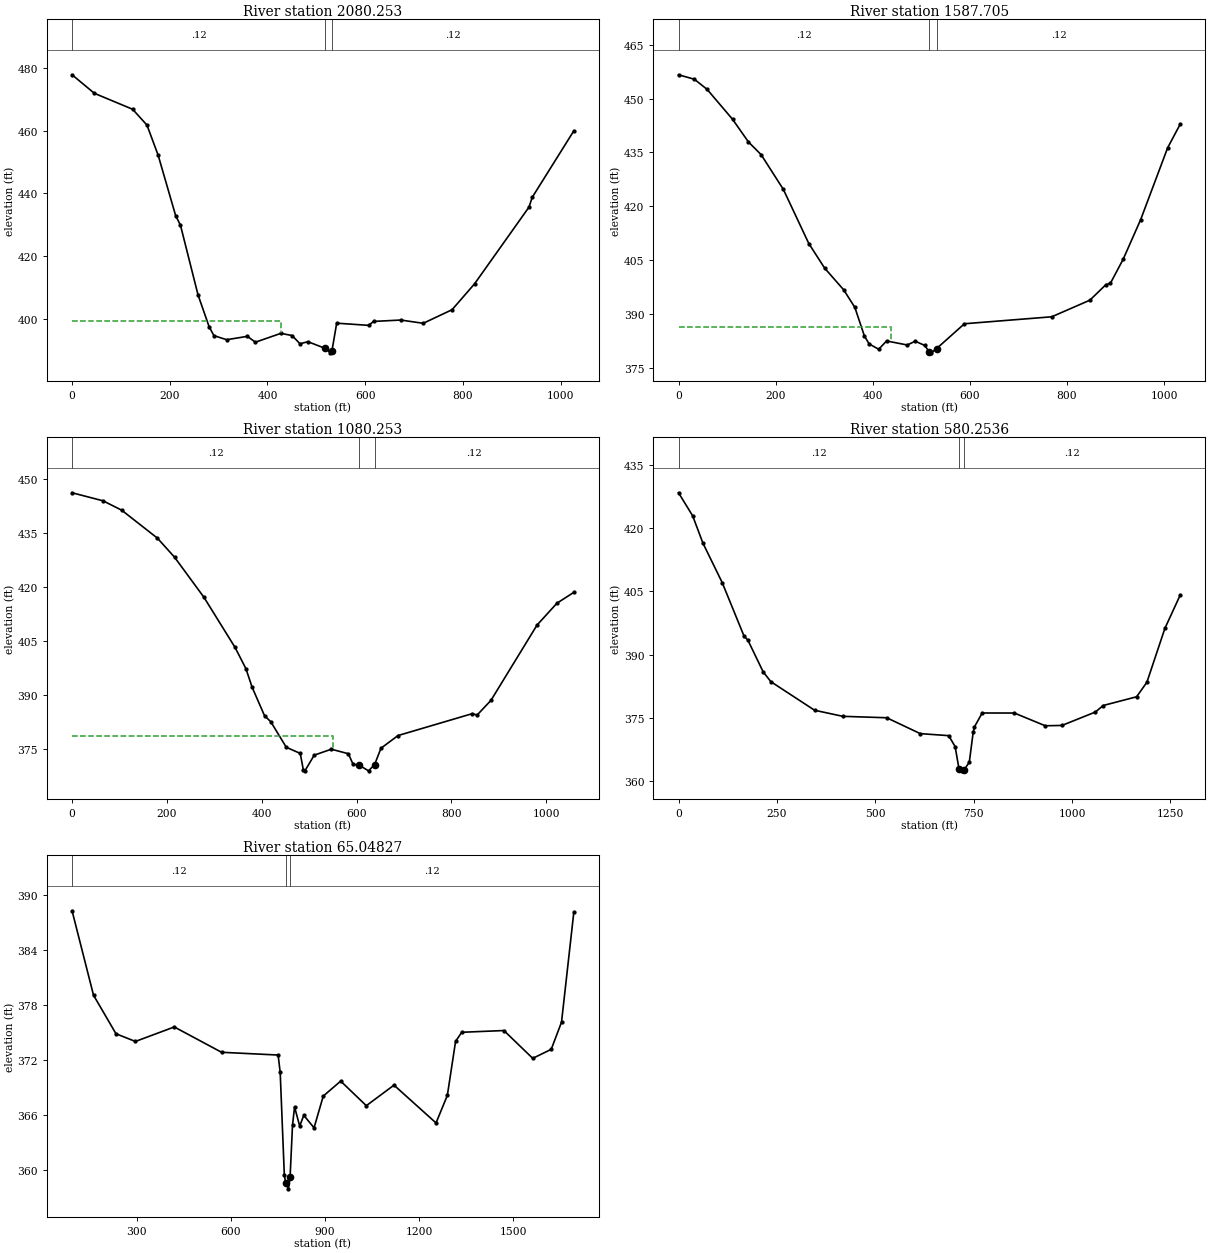
Type RM Length L Ch R = 1 ,2080.253,496.23,492.55,467.86
Node Name=975
XS GIS Cut Line= 3
2436633.62665194246674.2112999412436323.30771877247102.156966358
2436030.56322552 247505.86646077
#Sta/Elev= 30
       0  477.88   45.68  471.96     124  466.87  153.36  461.81  176.21  452.21
   212.1  432.89  221.89  429.87  257.78  407.66  280.62  397.42  290.41   394.6
  316.52   393.3  358.94  394.38  375.25   392.5  427.46  395.33   450.3  394.64
  466.62  392.01  482.93  392.66  518.83   390.5  528.62  389.11   531.9  389.61
  541.74  398.58  607.36  397.88   617.2  399.14  672.97  399.58   718.9  398.54
  777.96  402.88  823.89  411.12  935.43  435.63     942  438.74  1027.3     460
#Mann= 3 , 0 , 0
       0     .12       0  518.83    .045       0   531.9     .12       0
#XS Ineff= 2 , 0
          427.94  399.35
Permanent Ineff=
       F       F
Bank Sta=518.83,531.9
XS Rating Curve= 0 ,0
Exp/Cntr=0.3,0.1

Type RM Length L Ch R = 1 ,1587.705,483.57,507.45,506.66
Node Name=976
XS GIS Cut Line= 3
2436033.71282552246365.7811425182435958.08666444246880.376570016
2435883.45853285247388.181984857
#Sta/Elev= 30
       0  456.64   32.71  455.39   58.88  452.57  111.22  444.25  143.93  437.94
   170.1  434.39   215.9  424.71  268.24  409.65  300.95  402.78  340.21  396.73
  363.11  391.85  382.73  383.91  392.55  381.68  412.17   380.2  428.53  382.51
  471.06  381.38  487.41  382.44  507.04  381.26  516.69   379.4  520.12   379.2
  531.52   380.4  588.78   387.3  768.58  389.24  847.04  393.86  879.73  398.14
  889.54  398.61  915.69  405.27  951.65  416.28 1007.23  436.29 1033.38  442.95
#Mann= 3 , 0 , 0
       0     .12       0  516.69    .045       0  531.52     .12       0
#XS Ineff= 2 , 0
          438.08  386.52
Permanent Ineff=
       F       F
Bank Sta=516.69,531.52
XS Rating Curve= 0 ,0
Exp/Cntr=0.3,0.1

Type RM Length L Ch R = 1 ,1080.253,508.06,500,471.42
Node Name=977
XS GIS Cut Line= 4
2435968.97509411246339.2559331062435524.73844978246774.767201185
2435347.25225618246948.7675093562435338.61152545  247136.3429216
#Sta/Elev= 30
       0  446.09   65.48  443.85  104.78  441.24  180.08  433.47   216.1  428.19
  278.31  417.01   343.8  403.09  366.72  397.19  379.81  392.02  406.01   384.1
   419.1  382.45  451.85  375.34  481.31  373.63  487.86  369.02  491.14  368.79
  510.78  373.15   546.8   374.8  582.82  373.55  592.64  370.63  606.05  370.31
  625.38  368.79  638.15  370.53  651.54  375.07  687.51   378.6  844.49   384.7
   854.3  384.29  883.61  388.39  980.73  409.31 1022.82   415.4 1058.43  418.41
#Mann= 3 , 0 , 0
       0     .12       0  606.05    .045       0  638.15     .12       0
#XS Ineff= 2 , 0
          549.63  378.48
Permanent Ineff=
       F       F
Bank Sta=606.05,638.15
XS Rating Curve= 0 ,0
Exp/Cntr=0.3,0.1

Type RM Length L Ch R = 1 ,580.2536,426.88,515.21,480.18
Node Name=978
XS GIS Cut Line= 4
2435638.95869377245941.9854021822435298.45871861246194.634831265
 2435305.8980082246516.0383879392435318.15192069247045.493365765
#Sta/Elev= 30
       0  428.35   35.88  422.89   61.97  416.42  110.89  407.08  166.34  394.41
  176.12  393.44  215.26  385.87  234.83  383.57  345.72  376.81  417.47  375.37
  528.97  375.03  614.26  371.27  686.44  370.79  702.84   368.2  712.68  362.91
  719.24  362.45   725.8  362.67  738.92  364.53  748.75  371.62  752.02  372.89
  771.64  376.16  853.37  376.15  931.82  373.13  974.32  373.21 1059.32  376.39
 1078.93  377.93 1163.93     380 1190.09  383.44 1235.85  396.21 1275.08  404.17
#Mann= 3 , 0 , 0
       0     .12       0  712.68    .045       0   725.8     .12       0
Bank Sta=712.68,725.8
XS Rating Curve= 0 ,0
Exp/Cntr=0.3,0.1

Type RM Length L Ch R = 1 ,65.04827,65.14,65.05,67.09
Node Name=979
XS GIS Cut Line= 5
 2435413.8925077245699.9402996352435157.99115178245812.876736522
2435106.07426086246215.6466002762435047.22693761246672.184729189
2435254.56099145247073.928341839
#Sta/Elev= 30
   94.32  388.27  162.62  379.07  234.18  374.87  295.98  374.03  419.88  375.61
  570.54  372.85  750.66  372.55  757.21  370.65  770.31  359.53  774.35  358.62
   783.4  357.97  788.78  359.29  796.46  364.92  802.99  366.89  819.31  364.81
  832.37  365.98  865.02  364.62   894.4  368.08   949.9  369.71 1031.52  367.03
 1119.66  369.27 1253.56  365.15 1289.59  368.15  1315.8  374.04 1335.46  375.03
 1469.77  375.22  1561.5  372.19 1620.46  373.17 1653.22  376.13 1692.54  388.15
#Mann= 3 , 0 , 0
   94.32     .12       0  774.35    .045       0  788.78     .12       0
Bank Sta=774.35,788.78
XS Rating Curve= 0 ,0
Exp/Cntr=0.3,0.1

Chan Stop Cuts=-1
Use User Specified Reach Order=0
Composite Channel Slope=5